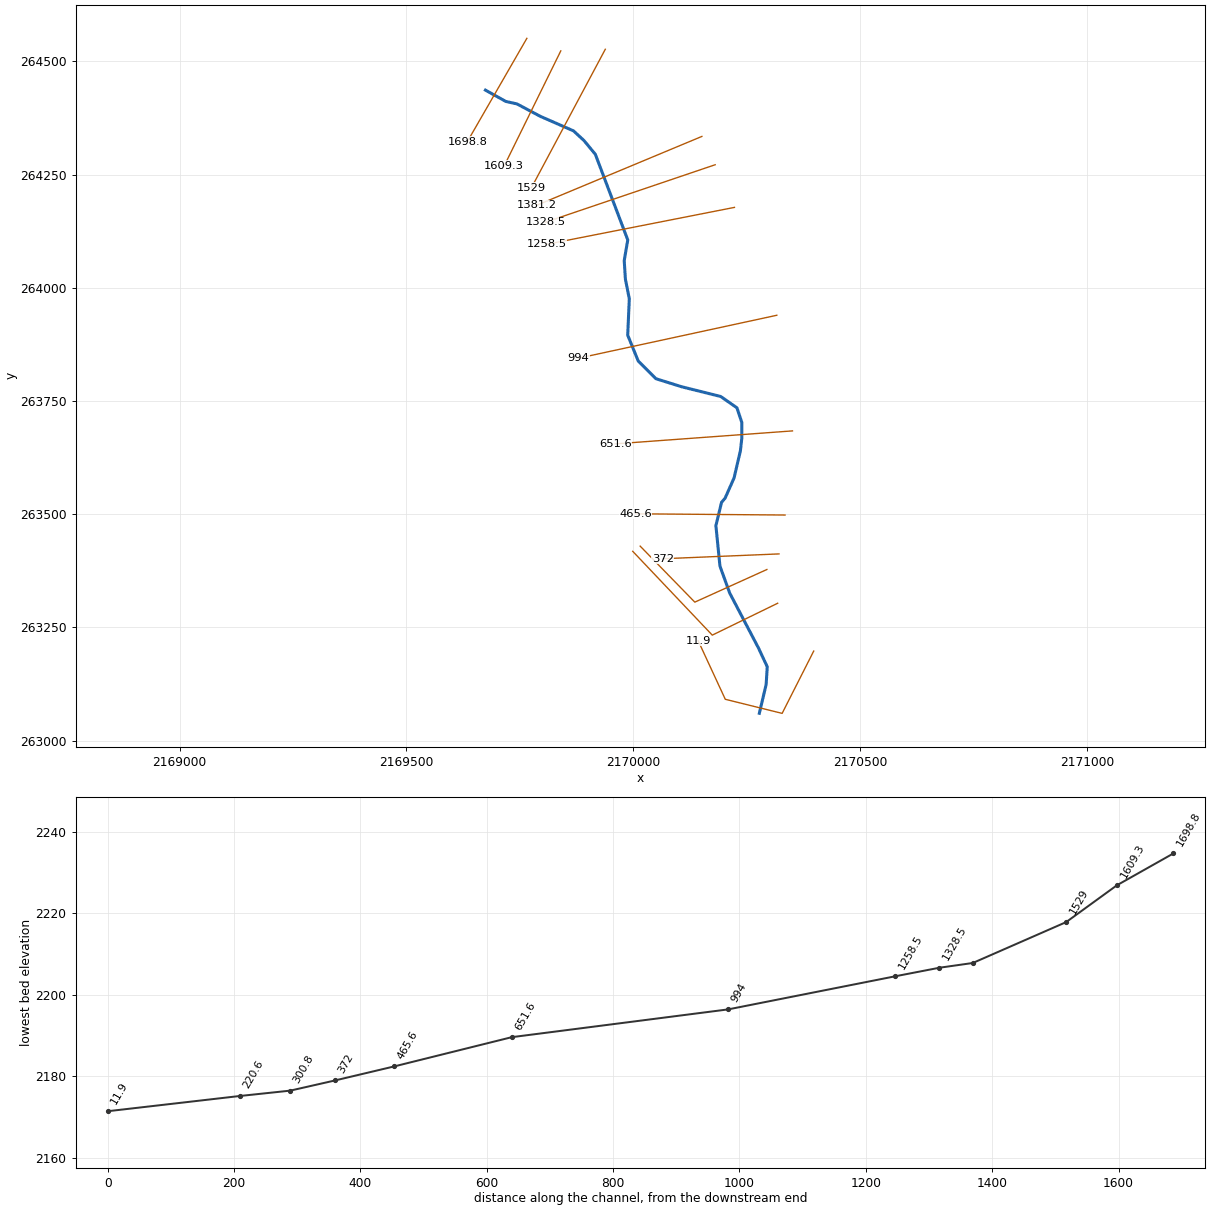
--- TuckaRunT2.prj (project) ---

Proj Title=TuckaRunT2
Current Plan=p01
Geom File=g01
Flow File=f01
Plan File=p01
DSS Export Rating Curves=0
DSS Export Rating Curve Sorted=0
DSS Export Volume Flow Curves=0
DXF OffsetX=0
DXF OffsetY=0
DXF ScaleX=0
DXF ScaleY=0

--- TuckaRunT2.p01 (plan) ---

Plan Title=Floodplain
Program Version=4.00
Geom File=g01
Flow File=f01
K Sum by GR=0
Std Step Tol=0.01
Critical Tol=0.01
Num of Std Step Trials=20
Max Error Tol=0.3
Flow Tol Ratio=0.001
Split Flow NTrial=30
Split Flow Tol=0.02
Split Flow Ratio=0.02
Log Output Level=0
Friction Slope Method=1
Unsteady Friction Slope Method=2
Unsteady Bridges Friction Slope Method=1
Global Log Level=0
CheckData=False
Run HTab=0
Run UNet=0
Run PostProcess=0
UNET Theta=0
UNET Theta Warmup=0
UNET ZTol=0
UNET ZSATol=0
UNET MxIter=0
UNET MaxInSteps=0
UNET DtIC=0
UNET DtMin=0
UNET MaxCRTS=0
UNET WFStab=0
UNET SFStab=0
UNET WFX=0
UNET SFX=0
UNET DSS MLevel=0
UNET DZMax Abort=0
UNET Convert EG Bridges=0
UNET Use Existing IB Tables=0
UNET Froude Limit=0
UNET Froude Power=0
Write IC File=0
Echo Input=False
Echo Output=False
Write Detailed=0

--- TuckaRunT2.f01 (steady flow) ---

Flow Title=NFF Regression Equation
Program Version=4.00
Number of Profiles=1
Profile Names=P100yr
River Rch & RM=TuckaRunT2,Main      ,1698.8
85.21811
River Rch & RM=TuckaRunT2,Main      ,1381.2
85.21811
River Rch & RM=TuckaRunT2,Main      ,994
562.1327
River Rch & RM=TuckaRunT2,Main      ,11.9
1740.814
Boundary for River Rch & Prof#=TuckaRunT2,Main      ,1
Up Type=0
Dn Type=3
Dn Slope=0.022375

--- TuckaRunT2.g01 (geometry) ---

Geom Title=USGS 10m DEM
Program Version=4.10

River Reach=TuckaRunT2      ,Main
Reach XY= 30
     2169674.012      264436.475     2169718.883      264411.561
     2169743.574      264405.991     2169794.912      264378.638
      2169868.01      264346.546     2169891.187      264325.151
     2169916.148      264294.842     2169987.602      264105.729
     2169979.798      264060.112     2169982.401       264019.12
     2169991.029      263975.705     2169987.463      263895.476
     2170010.641      263838.424     2170049.864        263799.2
     2170106.917      263781.371     2170192.495      263759.976
     2170228.153      263735.016      2170238.85      263702.924
      2170238.85      263667.266     2170235.821      263640.173
     2170221.802      263579.997     2170202.049      263535.443
     2170194.278      263526.418     2170181.798      263474.715
     2170190.712       263385.57     2170212.229      263325.957
     2170275.824      263204.237     2170294.971      263163.207
     2170292.547      263124.207     2170277.538      263060.486

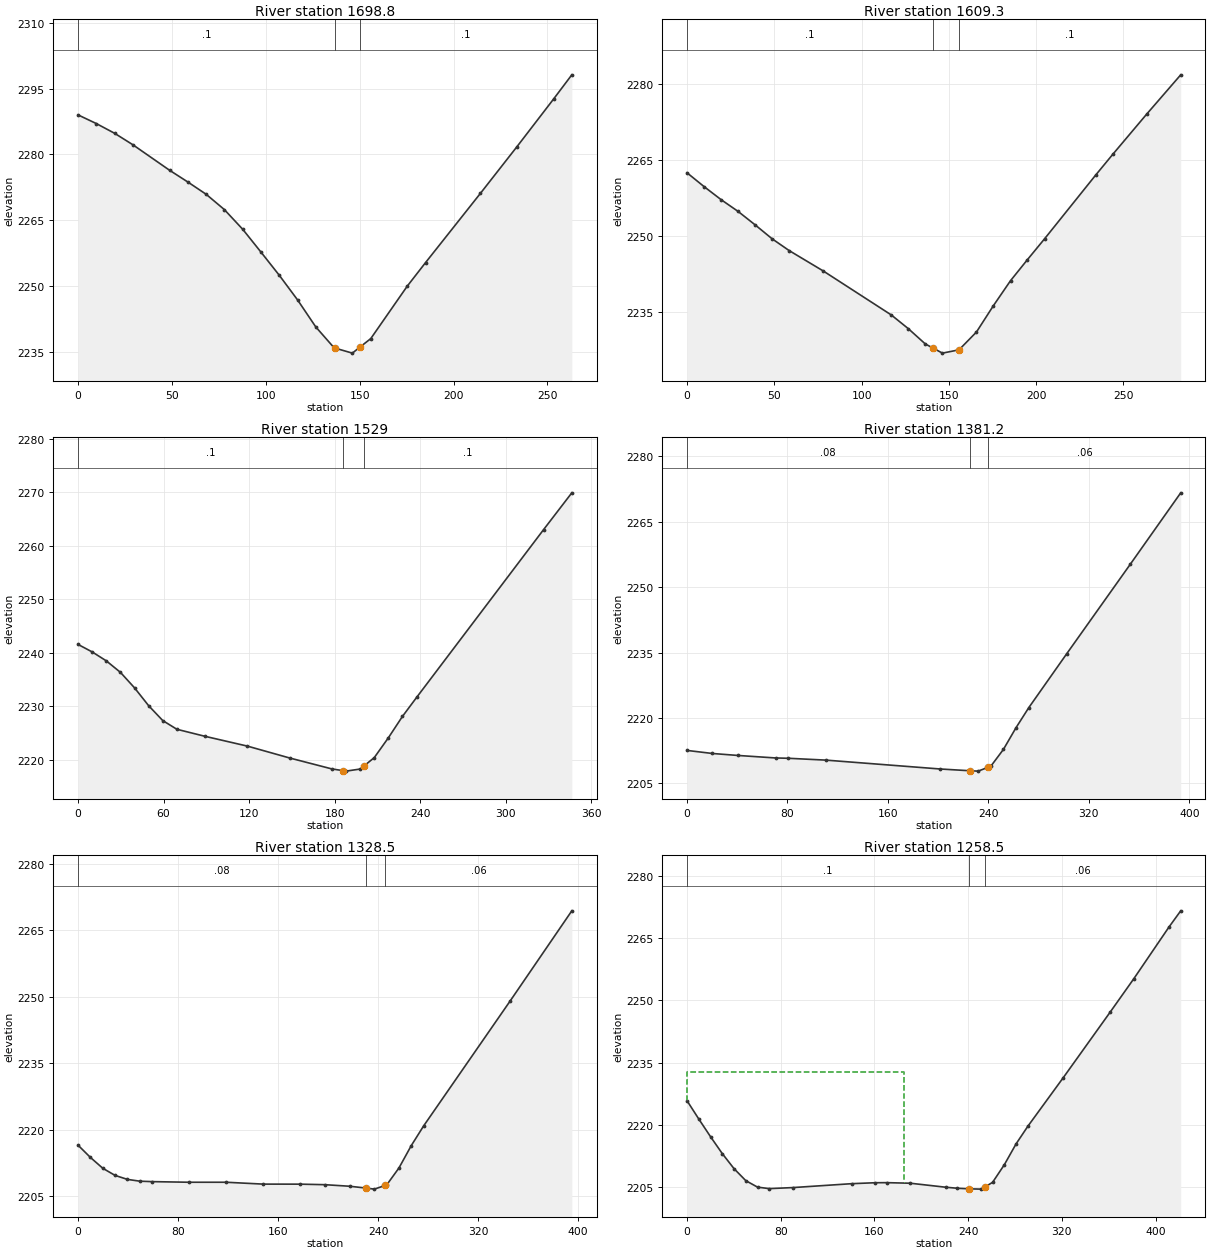
Type RM Length L Ch R = 1 ,1698.8  ,88,89.5,91
XS GIS Cut Line= 2
     2169765.259      264550.875     2169634.171      264322.856
#Sta/Elev= 24
       0    2289     9.7 2287.03    19.5  2284.8    29.2 2282.19    48.7 2276.39
    58.4 2273.72    68.2 2270.91    77.9 2267.42    87.7 2262.92    97.4 2257.73
   107.2 2252.42   116.9 2246.83   126.6 2240.67   136.4 2235.89   136.8 2235.84
   146.1 2234.69  150.18 2236.08   155.9    2238   175.3 2249.94   185.1 2255.34
   214.3 2271.11   233.8 2281.77   253.3 2292.63     263 2298.14
#Mann= 3 , 0 , 0
       0      .1       0   136.8    .045       0  150.18      .1       0
Bank Sta=136.8,150.18
XS Rating Curve= 0 ,0
Exp/Cntr=0.3,0.1

Type RM Length L Ch R = 1 ,1609.3  ,80.9,80.3,79.4
XS GIS Cut Line= 2
     2169840.035      264523.181     2169715.409      264269.313
#Sta/Elev= 23
       0 2262.48     9.8 2259.74    19.5 2257.18    29.3 2254.84      39  2252.2
    48.8 2249.43    58.5 2247.12      78  2243.1     117 2234.41   126.8 2231.69
   136.5 2228.68   140.8 2227.89   146.3 2226.87   155.8 2227.52   165.8 2231.04
   175.5 2236.24   185.3 2241.17     195 2245.33   204.8 2249.44     234 2261.99
   243.8 2266.09   263.3 2274.06   282.8 2281.82
#Mann= 3 , 0 , 0
       0      .1       0   140.8    .045       0   155.8      .1       0
Bank Sta=140.8,155.8
XS Rating Curve= 0 ,0
Exp/Cntr=0.3,0.1

Type RM Length L Ch R = 1 ,1529    ,163.4,147.8,132.3
XS GIS Cut Line= 2
     2169938.113      264526.719     2169775.332      264220.999
#Sta/Elev= 22
       0 2241.54     9.9 2240.14    19.8 2238.47    29.7 2236.32    39.6 2233.42
    49.5 2230.08    59.4  2227.3    69.3 2225.67    89.1 2224.35   118.8 2222.52
   148.4  2220.3   178.1 2218.25   185.6 2217.94     188 2217.84   197.9 2218.23
   200.6 2218.81   207.8 2220.37   217.7 2224.08   227.6 2228.09   237.5 2231.63
   326.6 2263.03   346.4 2269.91
#Mann= 3 , 0 , 0
       0      .1       0   185.6    .045       0   200.6      .1       0
Bank Sta=185.6,200.6
XS Rating Curve= 0 ,0
Exp/Cntr=0.3,0.1

Type RM Length L Ch R = 1 ,1381.2  ,54.2,52.7,51.1
XS GIS Cut Line= 2
     2170150.904      264334.252     2169788.113      264182.654
#Sta/Elev= 17
       0 2212.56    20.2 2211.86    40.3 2211.41    70.6 2210.83    80.6 2210.76
   110.9 2210.33   201.6  2208.3     225  2207.9   231.9 2207.81     240 2208.72
     242 2208.95     252  2212.8   262.1 2217.81   272.2 2222.38   302.4 2234.74
   352.9 2255.22   393.2 2271.66
#Mann= 3 , 0 , 0
       0     .08       0     225    .045       0     240     .06       0
Bank Sta=225,240
XS Rating Curve= 0 ,0
Exp/Cntr=0.3,0.1

Type RM Length L Ch R = 1 ,1328.5  ,73,70,66.9
XS GIS Cut Line= 2
      2170180.17      264271.729     2169806.155      264144.757
#Sta/Elev= 22
       0 2216.54     9.9 2213.78    19.8 2211.34    29.6 2209.74    39.5 2208.84
    49.4 2208.44    59.2 2208.34    88.9  2208.2   118.5  2208.2   148.1 2207.78
   177.7 2207.77   197.5 2207.65   217.2  2207.3   230.7 2206.88     237 2206.65
   245.7 2207.48   246.9  2207.6   256.7 2211.42   266.6 2216.48   276.5 2220.92
   345.6 2249.02     395 2269.36
#Mann= 3 , 0 , 0
       0     .08       0   230.7    .045       0   245.7     .06       0
Bank Sta=230.7,245.7
XS Rating Curve= 0 ,0
Exp/Cntr=0.3,0.1

Type RM Length L Ch R = 1 ,1258.5  ,264.1,264.5,264.7
XS GIS Cut Line= 2
     2170222.719      264177.578      2169809.15      264096.065
#Sta/Elev= 27
       0 2225.85      10 2221.46    20.1 2217.17    30.1 2213.11    40.2 2209.46
    50.2 2206.59    60.2 2205.03    70.2 2204.67    90.3 2204.92   140.5 2205.86
   160.6 2206.09   170.6 2206.11   190.7 2205.97   220.8 2205.01   230.8 2204.76
     241 2204.62   250.9 2204.55  254.02 2205.01   260.9 2206.19     271 2210.47
     281 2215.48     291  2219.7   321.2 2231.39   361.3  2247.2   381.4 2255.21
   411.5 2267.69   421.5 2271.58
#Mann= 3 , 0 , 0
       0      .1       0     241    .045       0  254.02     .06       0
#XS Ineff= 2 , 0
          185.37 2232.76
Permanent Ineff=
       F       F
Bank Sta=241,254.02
XS Rating Curve= 0 ,0
Exp/Cntr=0.3,0.1

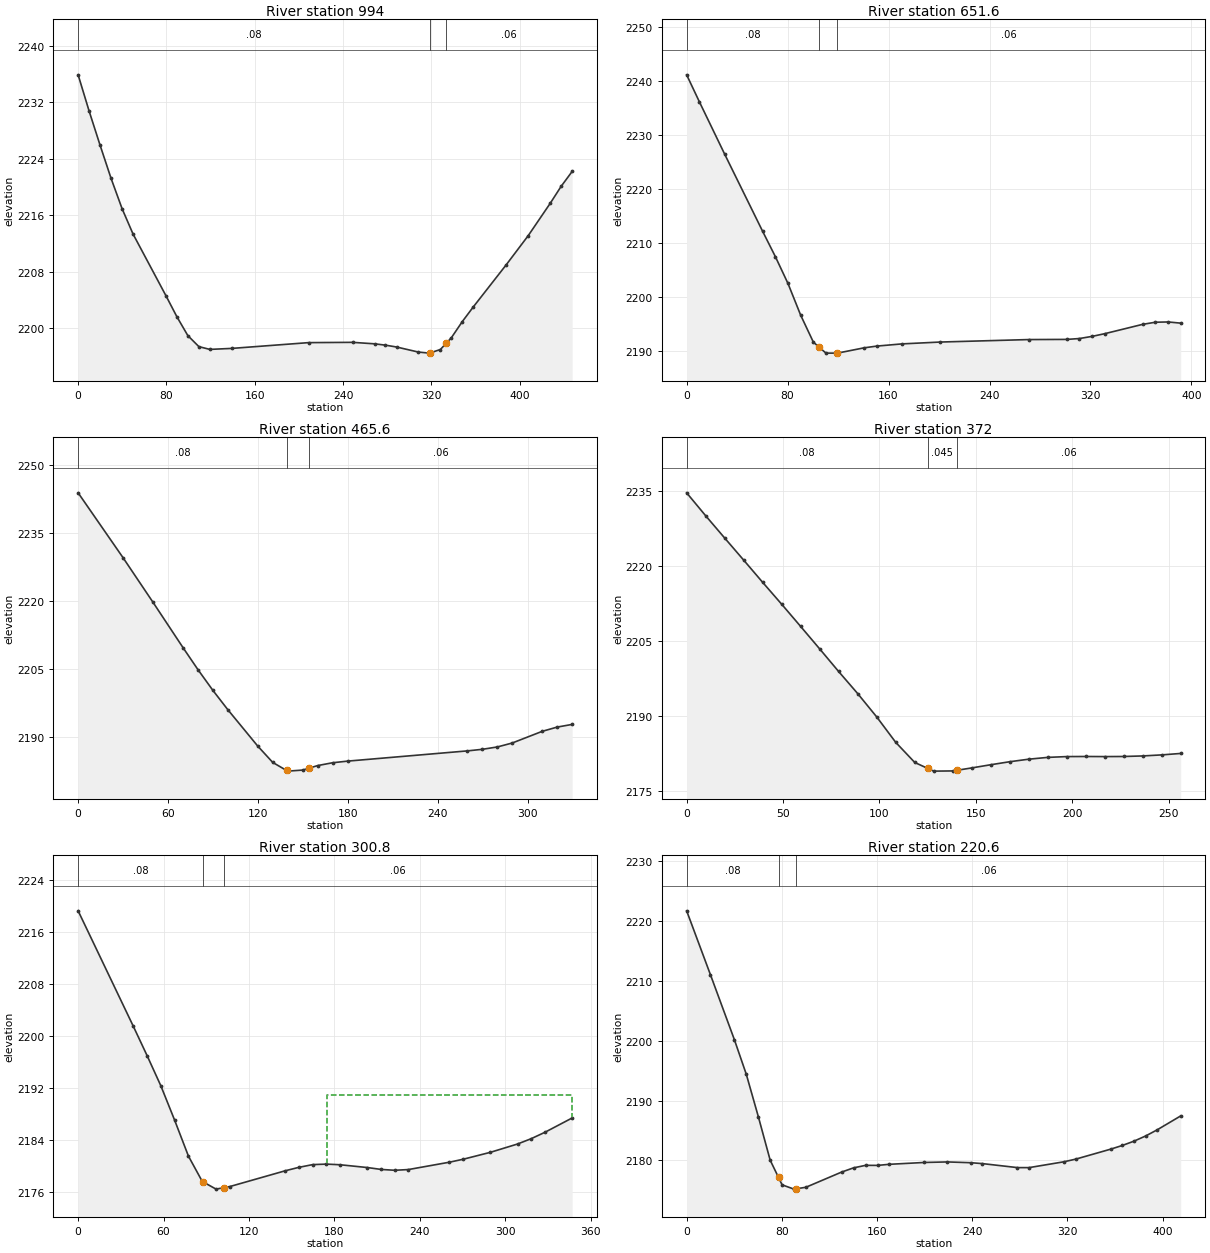
Type RM Length L Ch R = 1 ,994     ,345.9,342.3,339
XS GIS Cut Line= 2
     2170316.039      263939.368     2169878.746      263844.523
#Sta/Elev= 30
       0 2235.91     9.9  2230.8    19.9 2225.92    29.8 2221.24    39.8 2216.93
    49.7 2213.34    79.6 2204.56    89.5 2201.58    99.4 2198.91   109.4 2197.35
   119.3 2196.96   139.2  2197.1   208.8 2197.92   248.6 2197.96   268.5 2197.75
   278.4 2197.56   288.4  2197.3   308.2 2196.58   318.2 2196.43   318.3 2196.44
   328.1 2196.94   333.3 2197.81   338.1 2198.62     348 2200.91     358    2203
   387.8 2208.97   407.7  2213.1   427.6 2217.68   437.5 2220.09   447.5 2222.21
#Mann= 3 , 0 , 0
       0     .08       0   318.3    .045       0   333.3     .06       0
Bank Sta=318.3,333.3
XS Rating Curve= 0 ,0
Exp/Cntr=0.3,0.1

Type RM Length L Ch R = 1 ,651.6   ,187.4,186,184.2
XS GIS Cut Line= 2
     2170350.539      263684.034     2169960.045      263655.416
#Sta/Elev= 24
       0 2241.13      10 2236.18    30.1 2226.46    60.2 2212.17    70.3 2207.48
    80.3 2202.51    90.4 2196.62   100.4 2191.66   104.5 2190.82   110.4 2189.62
   119.5 2189.62   140.6  2190.6   150.6 2190.92   170.7 2191.33   200.8 2191.67
   271.1 2192.13   301.2 2192.16   311.2 2192.32   321.3 2192.72   331.3 2193.22
   361.4 2194.95   371.5 2195.34   381.5 2195.39   391.5 2195.17
#Mann= 3 , 0 , 0
       0     .08       0   104.5    .045       0   119.5     .06       0
Bank Sta=104.5,119.5
XS Rating Curve= 0 ,0
Exp/Cntr=0.3,0.1

Type RM Length L Ch R = 1 ,465.6   ,92.5,93.6,94.7
XS GIS Cut Line= 2
     2170334.235      263498.258     2170004.766      263500.993
#Sta/Elev= 23
       0 2243.93      30 2229.58    49.9 2219.77    69.9 2209.76    79.9 2204.88
    89.9 2200.28    99.8 2196.04   119.8 2187.98   129.8 2184.37     139  2182.6
   139.8 2182.45   149.8 2182.68     154  2183.1   159.8 2183.68   169.7  2184.3
   179.7 2184.66   259.6 2186.92   269.6 2187.27   279.6 2187.79   289.5 2188.66
   309.5 2191.24   319.5 2192.18   329.5 2192.77
#Mann= 3 , 0 , 0
       0     .08       0     139    .045       0     154     .06       0
Bank Sta=139,154
XS Rating Curve= 0 ,0
Exp/Cntr=0.3,0.1

Type RM Length L Ch R = 1 ,372     ,62.6,71.2,79.9
XS GIS Cut Line= 2
      2170320.93      263412.416     2170064.928      263401.727
#Sta/Elev= 29
       0 2234.72     9.8 2230.16    19.7 2225.68    29.6 2221.24    39.4 2216.81
    49.3 2212.41    59.1 2207.98      69 2203.47    78.8 2198.96    88.7 2194.53
    98.6 2189.84   108.4 2184.78   118.3 2180.74     125 2179.56   128.1 2179.01
     138 2179.05     140 2179.17   147.8 2179.65   157.7 2180.29   167.5 2180.89
   177.4  2181.4   187.2 2181.76   197.1 2181.92     207 2181.94   216.8 2181.92
   226.7 2181.94   236.5 2182.05   246.4 2182.26   256.2 2182.55
#Mann= 3 , 0 , 0
       0     .08       0     125    .045       0     140     .06       0
Bank Sta=125,140
XS Rating Curve= 0 ,0
Exp/Cntr=0.3,0.1

Type RM Length L Ch R = 1 ,300.8   ,79.5,80.2,80.8
XS GIS Cut Line= 3
      2170294.19      263377.982     2170135.344      263305.928
     2170014.982      263429.566
#Sta/Elev= 27
       0 2219.32    38.8 2201.54    48.4 2197.06    58.1  2192.4    67.8  2187.1
    77.5 2181.57    87.2 2177.68    87.6 2177.63    96.9  2176.5   102.6 2176.74
   106.6  2176.9   145.4 2179.32     155 2179.85   164.7 2180.27   174.4 2180.35
     184 2180.25   203.2 2179.82   212.8 2179.53   222.4  2179.4   231.9 2179.51
   260.7 2180.64   270.3 2181.09   289.5 2182.16   308.6 2183.44   318.2 2184.26
   327.8 2185.24     347 2187.45
#Mann= 3 , 0 , 0
       0     .08       0    87.6    .045       0   102.6     .06       0
#XS Ineff= 2 , 0
                          174.65         2191.05
Permanent Ineff=
       F       F
Bank Sta=87.6,102.6
XS Rating Curve= 0 ,0
Exp/Cntr=0.3,0.1

Type RM Length L Ch R = 1 ,220.6   ,224.6,208.7,192.6
XS GIS Cut Line= 3
     2170317.935      263303.472     2170173.828      263233.056
     2169998.606      263418.103
#Sta/Elev= 30
       0 2221.74      20 2211.05    40.1 2200.19    50.1 2194.41    60.2 2187.33
    70.2 2180.02    77.2 2177.14    80.2  2175.9    90.2 2175.18    92.2 2175.24
   100.2 2175.49   130.3 2178.04   140.3 2178.74   150.4 2179.16   160.4 2179.15
   170.2 2179.33   199.6 2179.64   219.2 2179.73   238.8  2179.6   248.6 2179.45
     278 2178.78   287.8 2178.78   317.2 2179.76     327  2180.2   356.4 2181.87
   366.2 2182.49     376 2183.21   385.8 2184.08   395.6 2185.12   415.2 2187.43
#Mann= 3 , 0 , 0
       0     .08       0    77.2    .045       0    92.2     .06       0
Bank Sta=77.2,92.2
XS Rating Curve= 0 ,0
Exp/Cntr=0.3,0.1

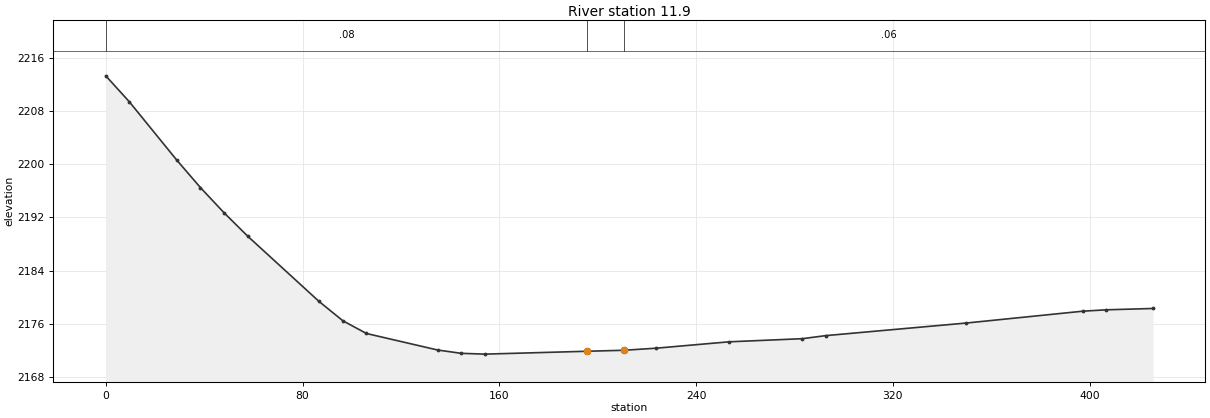
Type RM Length L Ch R = 1 ,11.9    ,11.6,11.9,12.2
XS GIS Cut Line= 4
     2170397.357      263197.848      2170327.76      263060.291
     2170202.485      263091.405     2170142.714      263220.774
#Sta/Elev= 22
       0 2213.27     9.6 2209.36    28.9 2200.59    38.5 2196.47    48.2 2192.65
    57.8 2189.14    86.7 2179.37    96.4 2176.46     106 2174.55   134.9 2172.07
   144.5 2171.57   154.2 2171.45   195.6 2171.88   210.6 2172.03   223.7 2172.34
   253.4  2173.3   283.2 2173.77   292.7 2174.23   349.8 2176.12   397.2  2177.9
   406.8 2178.11   425.8 2178.31
#Mann= 3 , 0 , 0
       0     .08       0   195.6    .045       0   210.6     .06       0
Bank Sta=195.6,210.6
XS Rating Curve= 0 ,0
Exp/Cntr=0.3,0.1

Chan Stop Cuts=-1
Use User Specified Reach Order=0
Composite Channel Slope=5